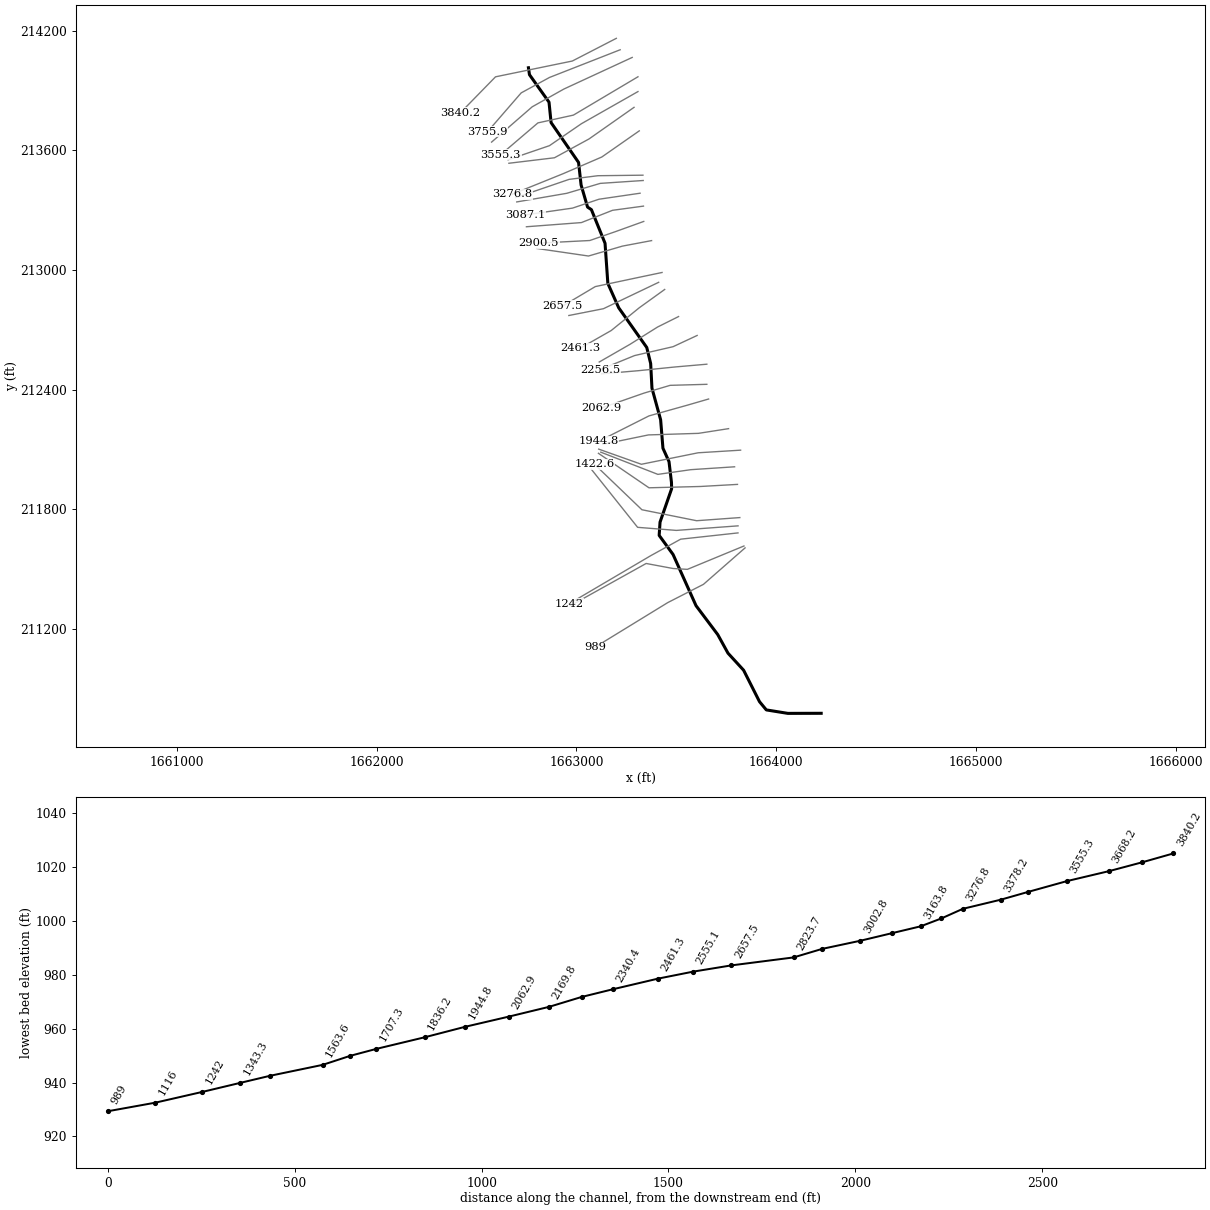
--- np4.prj (project) ---

Proj Title=np4
Current Plan=p01
Default Exp/Contr=0,0
English Units
Geom File=g01
Flow File=f01
Plan File=p01
BEGIN DESCRIPTION:
END DESCRIPTION:
DSS Export Rating Curves= 0
DSS Export Rating Curve Sorted= 0
DSS Export Volume Flow Curves= 0
DXF OffsetX= 0
DXF OffsetY= 0
DXF ScaleX= 0
DXF ScaleY= 0

--- np4.p01 (plan) ---

Plan Title=Floodplain
Program Version=4.00
Geom File=g01
Flow File=f01
K Sum by GR=0
Std Step Tol=0.01
Critical Tol=0.01
Num of Std Step Trials=20
Max Error Tol=0.3
Flow Tol Ratio=0.001
Split Flow NTrial=30
Split Flow Tol=0.02
Split Flow Ratio=0.02
Log Output Level=0
Friction Slope Method=1
Unsteady Friction Slope Method=2
Unsteady Bridges Friction Slope Method=1
Global Log Level=0
CheckData=False
Run HTab=0
Run UNet=0
Run PostProcess=0
UNET Theta=0
UNET Theta Warmup=0
UNET ZTol=0
UNET ZSATol=0
UNET MxIter=0
UNET MaxInSteps=0
UNET DtIC=0
UNET DtMin=0
UNET MaxCRTS=0
UNET WFStab=0
UNET SFStab=0
UNET WFX=0
UNET SFX=0
UNET DSS MLevel=0
UNET DZMax Abort=0
UNET Convert EG Bridges=0
UNET Use Existing IB Tables=0
UNET Froude Limit=0
UNET Froude Power=0
Write IC File=0
Echo Input=False
Echo Output=False
Write Detailed=0

--- np4.f01 (steady flow) ---

Flow Title=NFF Regression Equation
Program Version=4.00
Number of Profiles= 1
Profile Names=P100yr
River Rch & RM=np4,Main            ,3840.2
     358
River Rch & RM=np4,Main            ,1422.6
     392
River Rch & RM=np4,Main            ,1116
     526
River Rch & RM=np4,Main            ,295.6
     536
Boundary for River Rch & Prof#=np4,Main            , 1
Up Type= 0
Dn Type= 3
Dn Slope=0.018
DSS Import GetInterval= 0
DSS Import GetPeak= 0
DSS Import FillOption= 0

--- np4.g01 (geometry) ---

Geom Title=USGS 10m DEM
Program Version=4.00

River Reach=np4             ,Main
Reach XY= 30
     1662759.621      214014.322     1662764.765      213979.562
     1662862.585      213841.797      1662873.04      213739.151
     1663010.588      213539.241     1663023.207      213426.373
     1663055.612      213315.231      1663074.92      213302.354
     1663143.126      213133.697     1663157.195      212932.264
     1663211.549      212809.991     1663352.004      212610.828
     1663371.544      212530.445     1663378.042      212406.614
     1663421.467      212248.018     1663433.032      212105.359
     1663463.436      212038.008      1663475.73      211933.728
      1663476.45      211901.866     1663418.492      211734.596
     1663414.137      211667.975     1663483.641      211572.376
     1663598.741      211315.285     1663707.342      211170.438
     1663758.742      211077.014     1663836.938      210991.552
      1663916.57      210833.675     1663950.599      210792.393
     1664058.495      210774.997     1664225.337      210775.378

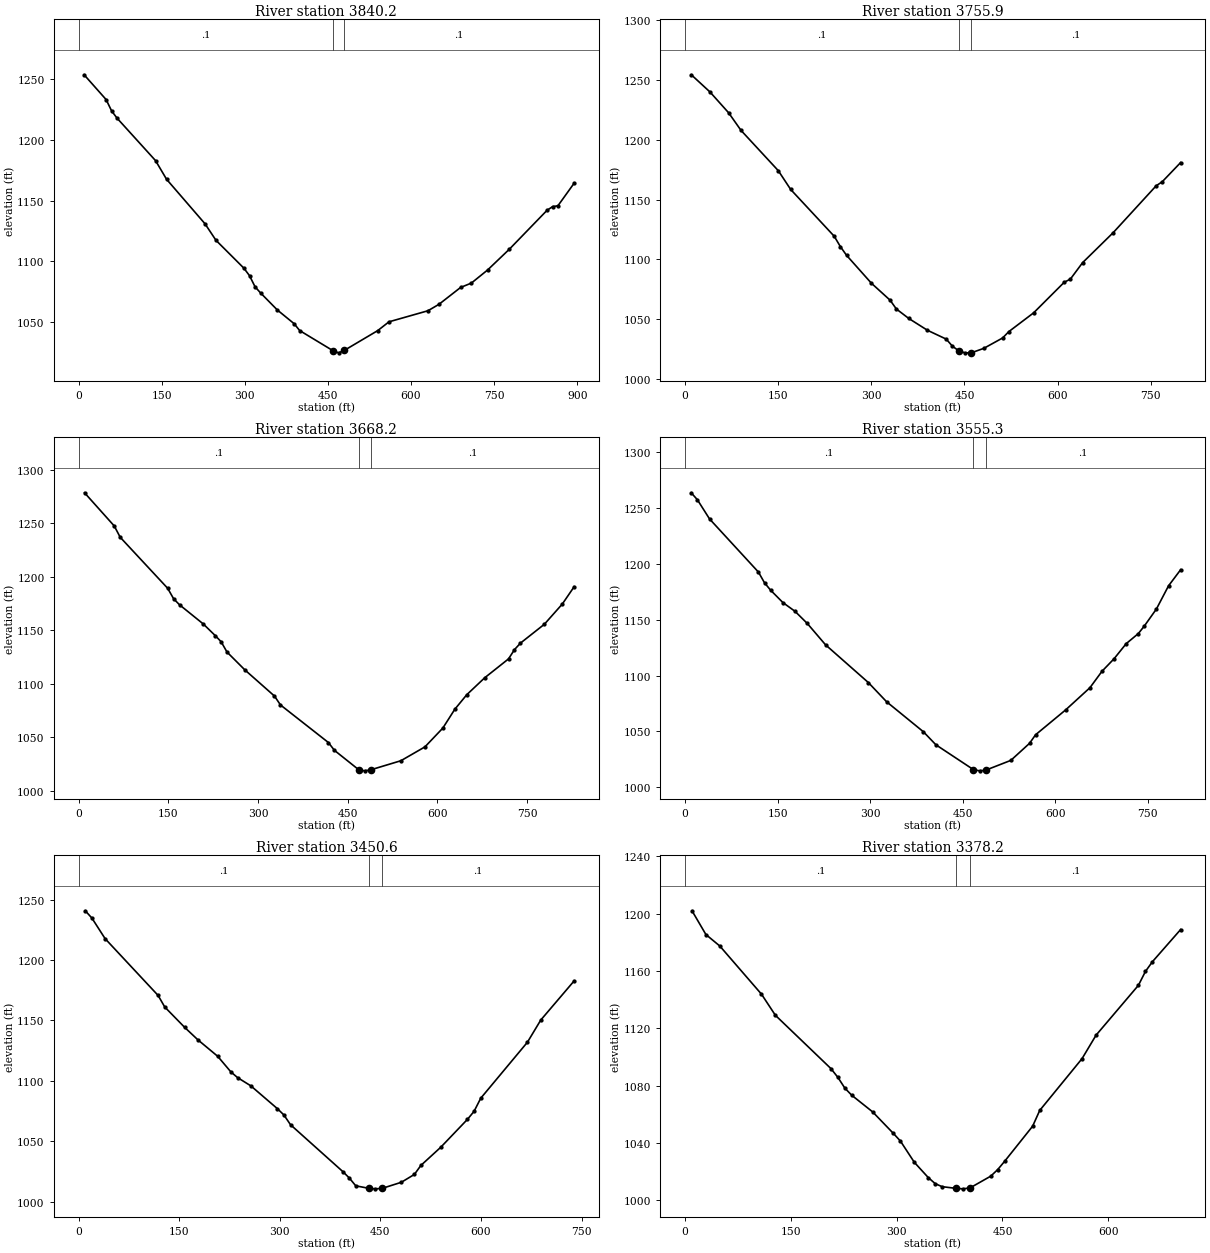
Type RM Length L Ch R = 1 ,3840.2  ,76.8,84.3,91.8
XS GIS Cut Line= 4
      1663199.65       214161.98     1662979.374      214048.163
     1662594.798      213968.917     1662417.661      213787.118
#Sta/Elev= 30
     9.9 1253.25    49.6  1232.9    59.5 1223.61    69.4 1217.61   138.8  1182.8
   158.7 1167.48   228.1 1130.93   247.9 1117.38   298.3 1094.48   308.4 1088.35
   318.4 1079.24   328.5 1074.11   358.7 1060.16   388.9 1048.94     399 1043.28
   459.4 1026.67   469.4    1025   479.4 1026.98   539.9 1043.27   560.1 1050.46
   630.5 1059.55   650.4 1064.84   689.4 1078.67   708.9 1082.27   738.2 1093.03
   777.3 1110.01   845.6 1142.08   855.4    1145   865.1 1145.73   894.4  1164.3
#Mann= 3 , 0 , 0
       0      .1       0   459.4    .045       0   479.4      .1       0
Bank Sta=459.4,479.4
XS Rating Curve= 0 ,0
Exp/Cntr=0.3,0.1

Type RM Length L Ch R = 1 ,3755.9  ,87.4,87.7,88
XS GIS Cut Line= 4
     1663218.884      214104.636       1662864.9      213965.665
     1662723.306      213888.313     1662555.491      213694.277
#Sta/Elev= 30
      10 1254.52      40 1240.17    70.1 1222.71    90.1 1207.94   150.1 1174.23
   170.1 1158.48   240.2 1119.31   250.2 1110.57   260.2 1103.27   300.2 1079.92
   330.2 1065.77   340.3  1058.4   360.3 1050.47   390.4 1040.57   420.6 1033.18
   430.7  1027.2   440.9 1023.36   450.9 1021.68   460.9 1021.69   481.1 1025.43
   511.4 1034.12   521.5 1039.47   561.4 1055.18   610.7 1080.78   620.6 1083.42
   640.3 1097.21   689.6 1122.34   758.7 1161.52   768.6 1164.97   798.2 1181.03
#Mann= 3 , 0 , 0
       0      .1       0   440.9    .045       0   460.9      .1       0
Bank Sta=440.9,460.9
XS Rating Curve= 0 ,0
Exp/Cntr=0.3,0.1

Type RM Length L Ch R = 1 ,3668.2  ,120.4,112.9,105.3
XS GIS Cut Line= 4
     1663279.167      214066.153     1662936.983      213907.516
     1662778.345      213818.365     1662575.133      213641.372
#Sta/Elev= 30
     9.9 1278.27    59.6 1247.23    69.5 1236.71   148.9 1189.01   158.8 1179.25
   168.7  1173.6   208.4  1155.7   228.3 1144.88   238.2 1139.12   248.1 1129.44
   277.9 1112.79   327.5  1088.3   337.5 1080.01   417.6 1044.91   427.7  1037.6
   468.3  1019.5   478.3 1018.44   488.3 1019.37   538.9 1027.89   579.1 1040.85
     609  1058.4     629 1075.97     649 1089.56   678.9 1105.35   718.8 1123.04
   728.8 1131.71   738.8 1137.79   778.7 1155.38   808.7 1174.26   828.6 1190.52
#Mann= 3 , 0 , 0
       0      .1       0   468.3    .045       0   488.3      .1       0
Bank Sta=468.3,488.3
XS Rating Curve= 0 ,0
Exp/Cntr=0.3,0.1

Type RM Length L Ch R = 1 ,3555.3  ,94.7,104.7,114.7
XS GIS Cut Line= 4
     1663308.011      213969.136     1662984.812      213776.785
     1662807.083      213737.699     1662621.019      213578.442
#Sta/Elev= 30
     9.9  1263.9    19.8 1257.74    39.6 1240.48   118.8 1192.87   128.7 1183.22
   138.6  1176.6   158.4 1165.56   178.2 1157.64     198  1146.8   227.6 1127.65
   296.9 1093.87   326.6 1076.59   386.2 1049.72   406.4 1038.08   467.2 1015.84
   477.2 1014.73   487.2 1015.34   527.8 1024.09   558.1 1039.35   567.9 1047.03
   616.9 1069.45     656 1089.21   675.6 1103.96   695.2 1115.22   714.8 1128.71
   734.4 1137.71   744.2 1144.53   763.8 1159.79   783.4 1180.53     803 1194.95
#Mann= 3 , 0 , 0
       0      .1       0   467.2    .045       0   487.2      .1       0
Bank Sta=467.2,487.2
XS Rating Curve= 0 ,0
Exp/Cntr=0.3,0.1

Type RM Length L Ch R = 1 ,3450.6  ,75.1,72.4,69.7
XS GIS Cut Line= 4
     1663308.035      213894.868     1663024.848      213733.609
       1662864.9       213623.48     1662657.753      213552.683
#Sta/Elev= 30
     9.9 1240.69    19.8 1234.65    39.5 1217.62   118.5 1170.67   128.4 1161.13
     158 1144.32   177.8 1133.97   207.4 1120.32   227.1 1107.39     237 1102.71
   256.8 1095.88   296.3 1077.06   306.1 1071.81     316 1063.72   393.9 1025.01
   403.6 1019.69   413.3 1013.18   432.4 1011.16   442.4 1010.69   452.4 1011.04
   481.2  1016.1   500.7 1022.61   510.4 1030.05     540 1045.07   579.8 1068.14
   589.7 1074.79   599.7 1085.66   669.3 1131.98   689.2 1150.32     739 1182.73
#Mann= 3 , 0 , 0
       0      .1       0   432.4    .045       0   452.4      .1       0
Bank Sta=432.4,452.4
XS Rating Curve= 0 ,0
Exp/Cntr=0.3,0.1

Type RM Length L Ch R = 1 ,3378.2  ,103.7,101.4,99
XS GIS Cut Line= 4
     1663288.345      213815.742     1663062.844      213657.105
     1662889.785      213562.709     1662661.662      213535.177
#Sta/Elev= 30
     9.8 1202.07    29.5 1185.48    49.2 1177.46   108.3 1143.82     128 1129.07
   206.8 1091.82   216.6 1085.72   226.5 1078.19   236.3  1073.2   265.9 1061.59
   295.4  1046.5   305.3 1041.21     325 1026.37   344.7 1015.74   354.6 1011.46
   364.4 1009.34     384 1008.18     394 1007.83     404 1008.48   433.4  1016.7
   443.3 1021.32   453.1  1027.1   492.8 1051.62   502.8  1062.6   562.8 1098.77
   582.7 1115.18   642.7 1149.98   652.7  1159.7   662.7 1166.55   702.6 1188.97
#Mann= 3 , 0 , 0
       0      .1       0     384    .045       0     404      .1       0
Bank Sta=384,404
XS Rating Curve= 0 ,0
Exp/Cntr=0.3,0.1

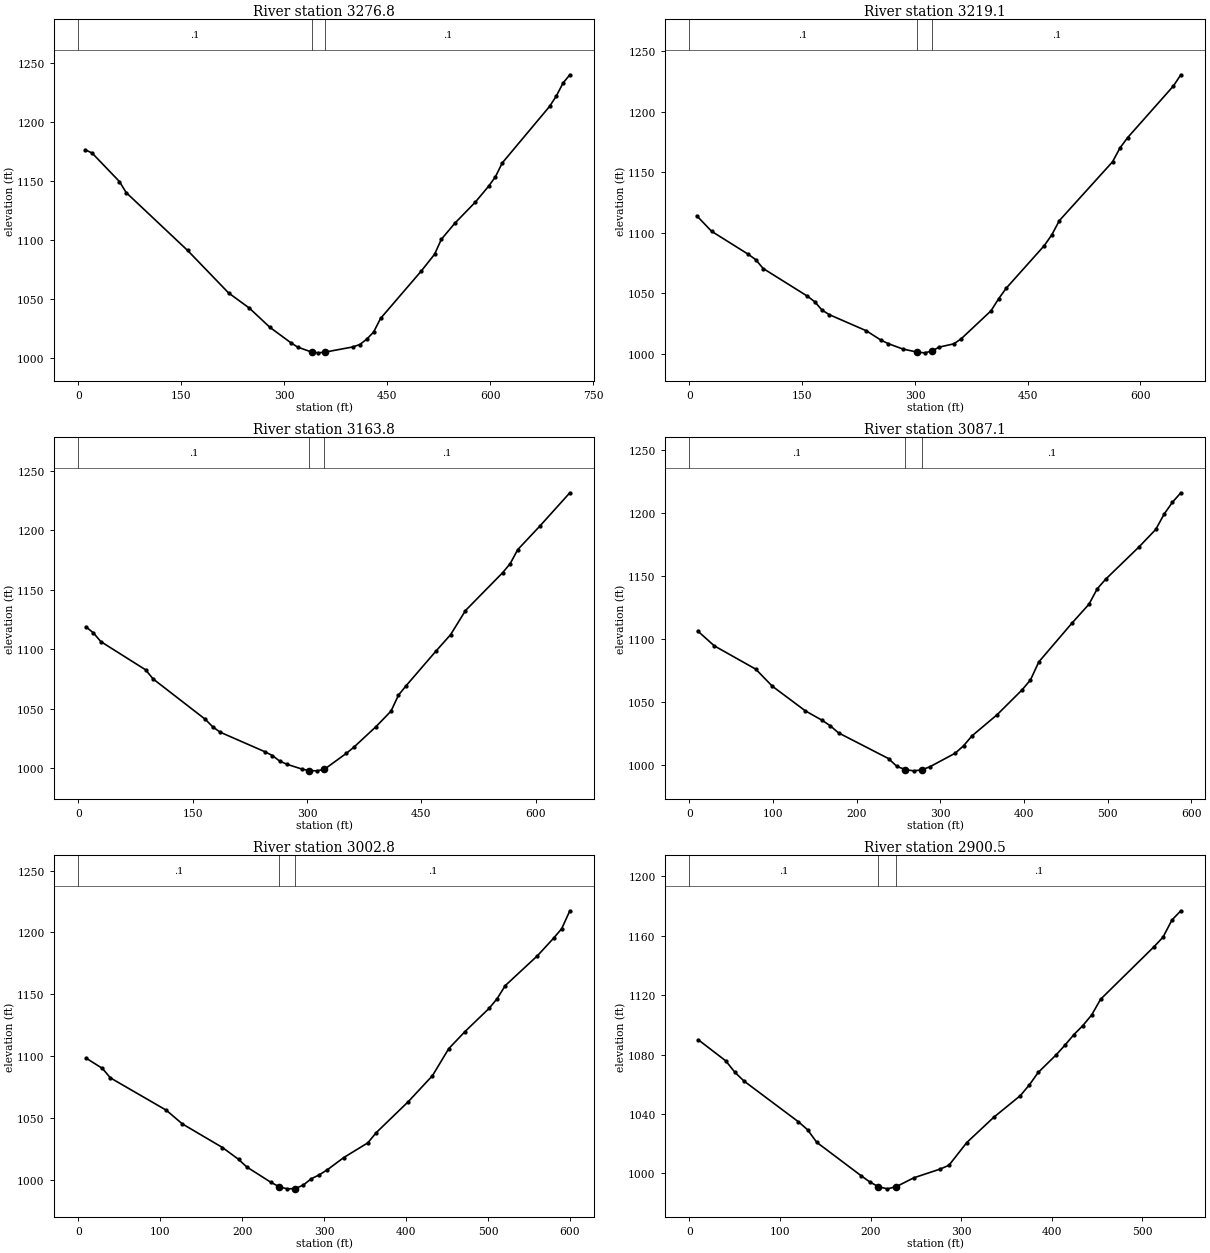
Type RM Length L Ch R = 1 ,3276.8  ,64.7,57.7,50.6
XS GIS Cut Line= 4
     1663314.566      213697.748     1663127.085      213566.643
      1662933.05      213482.735     1662677.394      213379.162
#Sta/Elev= 30
     9.9 1176.39    19.9 1173.66    59.7 1149.53    69.6 1140.15   159.1 1091.15
   218.8 1055.17   248.9  1042.4   279.1 1025.99   309.3  1013.1   319.4 1009.32
   339.6 1005.16   349.6 1004.45   359.6  1005.1   399.9 1009.45     410  1011.5
     420 1015.97   430.1 1022.05   440.2 1033.57   499.3 1073.57     519 1087.99
   528.8 1100.63   548.5 1114.22   578.1 1131.95   597.8 1145.65   607.6 1153.58
   617.5 1165.24   686.5 1213.15   696.3 1221.95   706.2 1233.02     716 1239.92
#Mann= 3 , 0 , 0
       0      .1       0   339.6    .045       0   359.6      .1       0
Bank Sta=339.6,359.6
XS Rating Curve= 0 ,0
Exp/Cntr=0.3,0.1

Type RM Length L Ch R = 1 ,3219.1  ,51.2,55.3,59.4
XS GIS Cut Line= 4
     1663332.945      213475.331     1663107.444      213472.709
     1662963.229      213454.355     1662695.774      213362.581
#Sta/Elev= 30
     9.8 1114.15    29.4 1101.37    78.4 1082.27    88.2 1077.87    98.1 1070.58
   156.9 1047.74   166.7 1043.08   176.5 1036.14   186.3 1032.36   235.2 1019.14
   254.6 1011.44   264.3 1008.53   283.7 1004.06   302.7 1001.49   312.7 1000.87
   322.7 1002.37   332.1 1005.59   351.5 1008.27   361.2  1012.3   401.2 1035.62
   411.3 1045.55   421.4 1054.29   471.9  1089.4     482 1098.36   492.1 1110.18
   562.8 1158.75   572.9 1170.38     583 1178.82   643.6  1221.3   653.7  1230.7
#Mann= 3 , 0 , 0
       0      .1       0   302.7    .045       0   322.7      .1       0
Bank Sta=302.7,322.7
XS Rating Curve= 0 ,0
Exp/Cntr=0.3,0.1

Type RM Length L Ch R = 1 ,3163.8  ,75.8,76.7,77.6
XS GIS Cut Line= 4
     1663334.232      213448.648     1663119.219      213434.226
     1662951.404      213384.406     1662700.993      213341.142
#Sta/Elev= 30
     9.8 1119.04    19.6 1113.91    29.4 1106.55    88.2 1082.81      98 1075.17
   166.5 1041.22   176.3 1034.88   186.1 1030.39   244.7 1013.98   254.4 1010.83
   264.1 1006.11   273.8 1003.42   293.3  999.42   302.7  998.17   312.7  997.95
   322.7  999.24   351.6 1012.71   361.4 1017.84   390.5 1035.15   410.1 1048.11
   419.9 1061.57   429.6 1069.24   468.7  1098.3   488.3  1112.4   507.8 1132.65
   556.7 1164.56   566.5 1172.13   576.3 1183.81   605.6  1203.8   644.7 1231.61
#Mann= 3 , 0 , 0
       0      .1       0   302.7    .045       0   322.7      .1       0
Bank Sta=302.7,322.7
XS Rating Curve= 0 ,0
Exp/Cntr=0.3,0.1

Type RM Length L Ch R = 1 ,3087.1  ,82.7,84.3,85.9
XS GIS Cut Line= 4
     1663318.524      213384.869     1663112.688      213354.715
     1662980.272      213310.139     1662742.972      213276.051
#Sta/Elev= 30
     9.9 1106.48    29.7 1094.67    79.3 1076.14    99.1  1062.6   138.7 1042.99
   158.5 1035.59   168.4 1031.18   178.3 1025.52     238 1005.15     248  998.95
   257.9  996.44   267.9  995.41   277.9  996.15   287.9  998.79   317.8 1009.44
   327.8 1015.34   337.8 1023.17   367.7 1039.89   397.7  1059.7   407.7 1067.56
   417.7 1081.92   457.6 1112.91   477.6 1127.65   487.6 1140.02   497.6 1147.57
   537.5 1173.22   557.5 1187.09   567.5 1199.22   577.5 1208.75   587.5  1216.2
#Mann= 3 , 0 , 0
       0      .1       0   257.9    .045       0   277.9      .1       0
Bank Sta=257.9,277.9
XS Rating Curve= 0 ,0
Exp/Cntr=0.3,0.1

Type RM Length L Ch R = 1 ,3002.8  ,103.3,102.3,101.2
XS GIS Cut Line= 4
     1663335.543      213320.165     1663180.838      213299.188
     1663024.823      213237.569     1662749.502      213216.592
#Sta/Elev= 30
     9.8 1098.11    29.3 1089.98      39 1082.34   107.3 1056.17   126.8 1045.16
   175.9 1026.01   195.6 1016.41   205.5 1010.31   235.1  997.85   244.8  994.41
   254.8  992.61   264.8   992.8   274.5  995.64   284.4  1000.8   294.3    1004
   304.1 1008.12   323.9 1017.88   353.4 1029.81   363.3 1037.84   402.8 1063.15
   432.3 1084.14   452.1 1105.93   471.8 1119.65   501.4 1138.54   511.2 1146.33
   521.1  1156.9   560.5 1181.12   580.3 1195.38   590.1 1203.01     600 1217.44
#Mann= 3 , 0 , 0
       0      .1       0   244.8    .045       0   264.8      .1       0
Bank Sta=244.8,264.8
XS Rating Curve= 0 ,0
Exp/Cntr=0.3,0.1

Type RM Length L Ch R = 1 ,2900.5  ,78.1,76.8,75.6
XS GIS Cut Line= 4
     1663336.878      213243.275     1663195.285      213192.144
     1663066.802      213147.568     1662811.146      213134.458
#Sta/Elev= 30
      10 1089.82    40.1 1075.73    50.2 1068.02    60.2 1062.16   120.4 1034.69
   130.5 1029.32   140.5 1020.92   189.4  998.49   199.1  994.25   208.5  991.03
   218.5  989.59   228.5  991.09   247.7  997.02   276.8  1002.9   286.5 1005.45
   306.2 1020.75   335.8 1037.68   365.3 1052.32   375.2 1059.51     385 1067.91
   404.7 1079.69   414.5 1086.25   424.4 1093.39   434.2  1099.4   444.1 1106.66
   453.9 1117.21     513 1152.63   522.8 1158.98   532.7 1170.56   542.5 1176.75
#Mann= 3 , 0 , 0
       0      .1       0   208.5    .045       0   228.5      .1       0
Bank Sta=208.5,228.5
XS Rating Curve= 0 ,0
Exp/Cntr=0.3,0.1

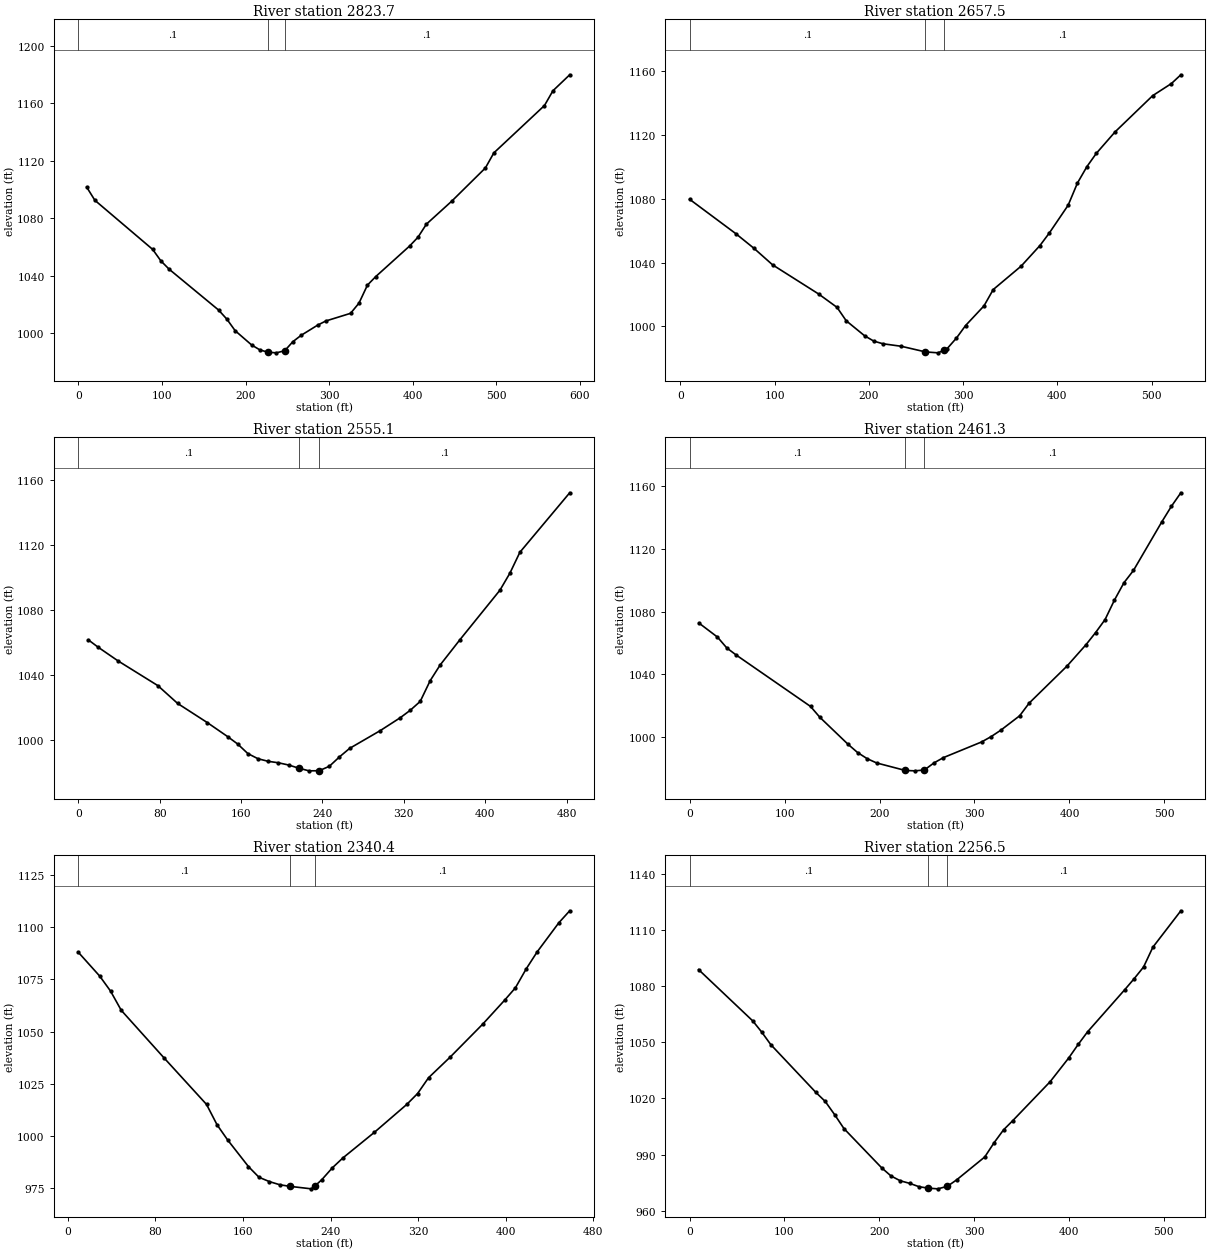
Type RM Length L Ch R = 1 ,2823.7  ,168,166.2,164.4
XS GIS Cut Line= 4
     1663376.185      213147.106     1663230.658      213119.574
     1663060.222      213069.754     1662800.633      213107.774
#Sta/Elev= 30
     9.9 1101.63    19.7 1092.47    88.9 1058.31    98.7 1050.34   108.6 1044.55
   167.8 1016.15   177.7 1009.81   187.6  1001.8   207.3  991.88   217.2  988.45
   226.9  986.84   236.9  986.41   246.9  987.88   256.6  994.13   266.5  998.57
   286.2 1005.63   296.1 1008.56   325.7 1013.88   335.8 1020.98   345.9  1033.5
   355.9 1039.46   396.3 1060.64   406.4 1066.79   416.5  1075.9   446.8 1091.87
   487.1 1114.97   497.2 1125.44   557.8 1158.38   567.9 1168.62     588 1179.75
#Mann= 3 , 0 , 0
       0      .1       0   226.9    .045       0   246.9      .1       0
Bank Sta=226.9,246.9
XS Rating Curve= 0 ,0
Exp/Cntr=0.3,0.1

Type RM Length L Ch R = 1 ,2657.5  ,96.4,102.4,108.4
XS GIS Cut Line= 4
     1663428.627      212987.158     1663304.077      212960.937
     1663094.309      212916.361     1662931.739      212819.343
#Sta/Elev= 30
     9.8 1079.79    58.7 1058.29    78.3 1048.94    97.9 1038.65   146.8 1020.35
   166.3 1011.97     176 1003.59   195.5  994.18   205.3  990.81     215  989.15
   234.5  987.57  260.14  984.04   273.5  983.46  279.92  985.19   283.2  986.15
     293  992.73   302.7  1000.6   322.2  1012.9     332 1023.13   361.7 1037.88
   381.6 1050.76   391.6 1058.67   411.5 1076.03   421.4 1089.98   431.4 1100.22
   441.4 1108.56   461.3 1122.03   501.2 1144.75   521.1 1152.36   531.1 1157.85
#Mann= 3 , 0 , 0
     9.8      .1       0  260.14    .045       0  279.92      .1       0
Bank Sta=260.14,279.92
XS Rating Curve= 0 ,0
Exp/Cntr=0.3,0.1

Type RM Length L Ch R = 1 ,2555.1  ,87.9,93.8,99.8
XS GIS Cut Line= 4
     1663411.608        212937.8      1663288.37      212878.803
     1663134.976      212805.384     1662961.917      212771.296
#Sta/Elev= 30
     9.8 1061.67    19.5 1057.14      39 1048.75    78.1 1033.56    97.6 1022.58
   126.9 1010.75   146.6 1002.25   156.6  997.64   166.6  991.76   176.6  988.58
   186.6     987   196.7  986.09   206.7  984.72   216.7  982.78   226.7  981.14
   236.7  981.21   246.7  983.93   256.7  989.72   266.7  994.96   296.7 1005.84
   316.5 1013.82   326.3 1018.39   336.1 1023.85   345.9 1036.61   355.7 1046.25
   375.3 1061.91   414.5 1092.26   424.3 1102.74   434.1 1115.57   483.1 1152.17
#Mann= 3 , 0 , 0
       0      .1       0   216.7    .045       0   236.7      .1       0
Bank Sta=216.7,236.7
XS Rating Curve= 0 ,0
Exp/Cntr=0.3,0.1

Type RM Length L Ch R = 1 ,2461.3  ,123.9,120.8,117.8
XS GIS Cut Line= 4
     1663441.738      212901.939     1663314.566      212810.166
     1663174.283      212696.104     1663018.268      212606.952
#Sta/Elev= 30
     9.8 1072.81    29.4 1063.83    39.2 1056.92      49 1052.44   127.4  1019.6
   137.2 1012.69   166.9  995.47   176.9  990.23     187  986.31     197  983.57
   227.2  978.79   237.2  978.55   247.2  979.07   257.3  983.58   267.3  986.98
   307.5  996.97   317.5 1000.36   327.6 1004.41   347.6 1013.66   357.6 1021.75
   397.5 1045.39   417.5 1059.03   427.5 1066.69   437.5 1074.99   447.4 1087.45
   457.4 1098.49   467.4 1106.32   497.4 1137.45   507.3 1147.17   517.3 1155.84
#Mann= 3 , 0 , 0
       0      .1       0   227.2    .045       0   247.2      .1       0
Bank Sta=227.2,247.2
XS Rating Curve= 0 ,0
Exp/Cntr=0.3,0.1

Type RM Length L Ch R = 1 ,2340.4  ,92.4,84,75.6
XS GIS Cut Line= 4
     1663511.248      212766.052     1663406.364       212713.61
     1663268.704      212627.081        1663114.      212537.929
#Sta/Elev= 30
     9.8 1087.99    29.3 1076.58    39.1 1069.46    48.9 1060.22    87.9 1037.44
   126.8 1015.08   136.4 1005.31     146  998.09   165.1  985.26   174.7  980.15
   184.2  978.08   193.8  976.55   203.3  975.78   222.5  974.61  226.06  976.14
     232  978.97   241.6  984.65   251.2  989.39   279.9 1001.64   309.6 1015.08
   319.5 1020.31   329.5 1027.88   349.3 1037.81   379.1 1053.66   398.9 1065.03
   408.8 1070.99   418.7 1080.11   428.7 1088.25   448.5 1102.21   458.4 1107.94
#Mann= 3 , 0 , 0
     9.8      .1       0   203.3    .045       0  226.06      .1       0
Bank Sta=203.3,226.06
XS Rating Curve= 0 ,0
Exp/Cntr=0.3,0.1

Type RM Length L Ch R = 1 ,2256.5  ,89.8,86.6,83.5
XS GIS Cut Line= 4
     1663604.308      212671.194     1663483.691      212614.819
     1663290.967      212570.243     1663117.908      212499.446
#Sta/Elev= 30
     9.5 1088.78    66.6 1061.39    76.1  1055.4    85.6 1048.74   133.1 1023.25
     143 1018.41   152.9 1011.37   162.8 1003.88   202.4  983.02   212.3  978.63
   222.2  976.02     232  974.68   241.9  972.88   251.7   972.1   261.7  971.74
   271.7  973.07   281.5  976.51   311.2  988.76   321.1  996.41     331 1003.24
   340.8 1008.19   380.2 1028.98   399.8 1041.67   409.7 1048.85   419.5 1055.52
   458.9 1078.13   468.7 1083.93   478.6 1090.16   488.4 1100.73   517.9 1120.17
#Mann= 3 , 0 , 0
       0      .1       0   251.7    .045       0   271.7      .1       0
Bank Sta=251.7,271.7
XS Rating Curve= 0 ,0
Exp/Cntr=0.3,0.1

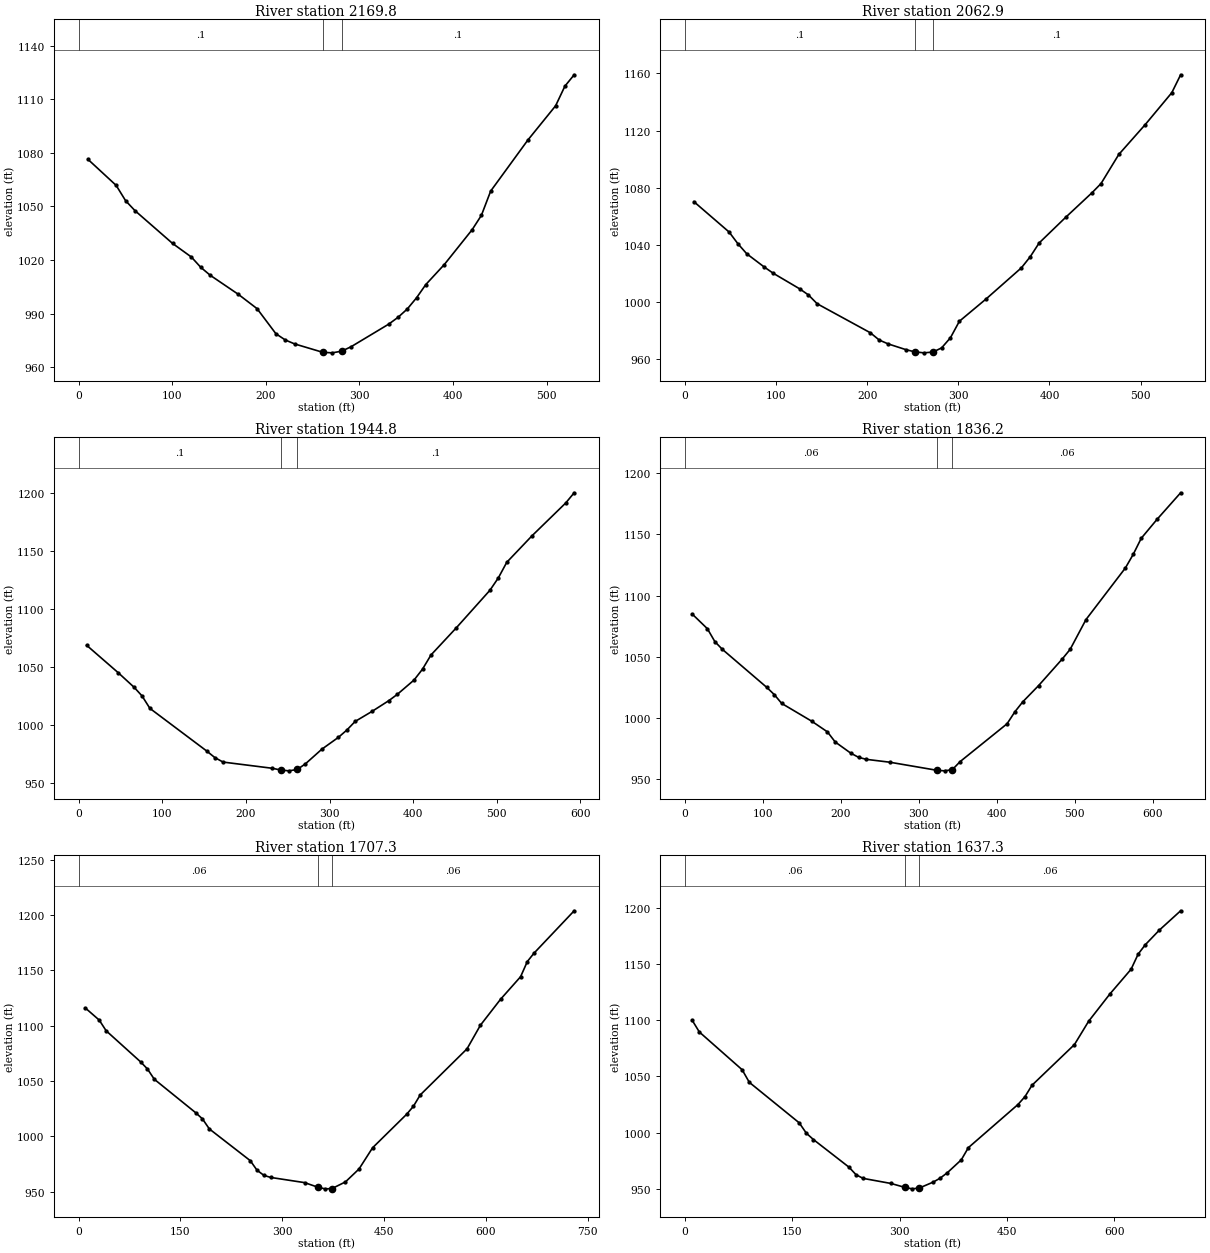
Type RM Length L Ch R = 1 ,2169.8  ,102.1,106.9,111.7
XS GIS Cut Line= 4
     1663652.817      212526.978     1663492.894      212513.019
     1663313.279      212494.664     1663125.774      212478.469
#Sta/Elev= 30
      10 1076.33    40.1 1061.77    50.2 1053.19    60.2 1047.64   100.3 1029.32
   120.4 1021.71   130.4 1015.97   140.5 1011.51   170.6 1000.82   190.6  992.81
   210.7  978.79   220.7   975.3   230.7  973.08   260.9  968.37   270.9  968.09
   280.9  969.02   290.9  971.47   331.1  984.11   341.1  987.93     351   992.6
   360.9  998.86   370.8 1006.28   390.6  1017.5   420.3 1036.97   430.2 1045.01
   440.1 1058.58   479.8 1087.13   509.5 1106.34   519.4 1117.31   529.3 1123.67
#Mann= 3 , 0 , 0
       0      .1       0   260.9    .045       0   280.9      .1       0
Bank Sta=260.9,280.9
XS Rating Curve= 0 ,0
Exp/Cntr=0.3,0.1

Type RM Length L Ch R = 1 ,2062.9  ,118.6,118.2,117.8
XS GIS Cut Line= 4
     1663652.817      212426.027     1663469.167      212420.906
     1663337.897       212381.82     1663127.085      212308.033
#Sta/Elev= 30
     9.7  1070.2    48.3    1049      58 1040.78    67.7 1033.77      87 1024.46
    96.7 1020.18   125.7 1009.28   135.4 1004.99     145  998.82   203.3  978.55
   213.1  973.46   222.9  970.74   242.4  966.72     252  965.21     262  964.49
     272  965.02   281.6  967.95   291.3  975.04   301.1  986.58   330.4 1002.16
   369.2 1023.96     379 1031.81   388.7 1041.37   417.8 1059.28   446.9 1076.59
   456.6 1082.89   476.1 1103.24   505.2 1124.19   534.3 1146.45     544 1158.98
#Mann= 3 , 0 , 0
       0      .1       0     252    .045       0     272      .1       0
Bank Sta=252,272
XS Rating Curve= 0 ,0
Exp/Cntr=0.3,0.1

Type RM Length L Ch R = 1 ,1944.8  ,114.6,108.5,102.5
XS GIS Cut Line= 4
     1663661.645      212352.322       1663552.5      212320.611
     1663362.971      212267.513     1663111.353      212140.218
#Sta/Elev= 30
     9.5 1068.74    47.4 1045.05    66.3 1032.59    75.8 1025.14    85.2 1014.42
     153   977.8   162.9  972.05   172.7  968.21   231.8  962.85   241.4   961.4
   251.4  960.67   261.4  961.85   271.1  966.65   290.8  979.29   310.5  989.43
   320.6  995.69   330.6 1003.16   350.8 1011.81   370.9 1021.07     381 1026.45
   401.1 1038.84   411.2  1048.2   421.3 1060.35   451.5 1083.66   491.8 1116.05
   501.8 1126.65   511.9 1140.09   542.1 1162.91   582.4 1191.14   592.5 1199.91
#Mann= 3 , 0 , 0
       0      .1       0   241.4    .045       0   261.4      .1       0
Bank Sta=241.4,261.4
XS Rating Curve= 0 ,0
Exp/Cntr=0.3,0.1

Type RM Length L Ch R = 1 ,1836.2  ,124.5,128.9,133.3
XS GIS Cut Line= 4
     1663761.659      212203.611     1663610.888      212180.012
     1663360.477      212172.146     1663132.354      212124.948
#Sta/Elev= 30
     9.5 1084.69    28.6 1072.94    38.2 1062.39    47.7 1056.14   104.9 1024.95
   114.5 1019.07     124 1011.87   162.6  997.31   182.7  988.62   192.7  980.34
   212.7  971.21   222.8  967.77   232.8  966.15   262.8  963.82     323  957.24
     333  956.77     343  957.71     353   964.3   413.3  995.24   423.4 1005.09
   433.5  1013.2   453.8 1026.47   484.2 1048.24   494.3 1056.09   514.6 1080.41
   565.2  1122.6   575.3 1133.77   585.5 1146.81   605.7 1162.23   636.1 1184.03
#Mann= 3 , 0 , 0
       0     .06       0     323    .045       0     343     .06       0
Bank Sta=323,343
XS Rating Curve= 0 ,0
Exp/Cntr=0.3,0.1

Type RM Length L Ch R = 1 ,1707.3  ,71.5,70,68.6
XS GIS Cut Line= 4
     1663821.943      212095.642     1663609.553      212082.532
     1663325.054      212024.845     1663111.353      212100.886
#Sta/Elev= 30
    10.1 1115.92    30.4 1105.07    40.5 1095.46    91.2 1067.36   101.3 1060.95
   111.5 1051.57   172.3 1021.38   182.4 1015.74   192.5 1006.69   252.8  977.97
   262.8   969.3   272.9  964.67   282.9  962.79   332.9  958.09   352.9  953.85
   362.9  952.48   372.9  952.65     393  958.75     413  970.44     433  989.64
   483.1  1019.9   493.1 1027.13   503.1 1037.36   572.1 1079.13   591.8 1100.46
   621.4 1123.88     651 1144.35   660.9 1158.05   670.7 1165.61   729.9 1203.97
#Mann= 3 , 0 , 0
       0     .06       0   352.9    .045       0   372.9     .06       0
Bank Sta=352.9,372.9
XS Rating Curve= 0 ,0
Exp/Cntr=0.3,0.1

Type RM Length L Ch R = 1 ,1637.3  ,76.6,73.7,70.8
XS GIS Cut Line= 4
     1663791.813      212012.197     1663572.868      211997.776
     1663407.675      211974.177     1663121.866      212085.616
#Sta/Elev= 30
      10    1100    19.9 1089.66    79.8 1056.01    89.8  1044.8   159.6 1008.71
   169.6  999.46   179.5  993.81   229.2  969.22   239.1  962.49   248.9  959.23
   288.1  954.67   307.6  951.16   317.6   949.9   327.6  950.63     347   955.9
   356.8  959.44   366.7  964.21   386.3  975.74   396.2  986.59   465.5 1024.98
   475.4 1032.06   485.2 1042.19   544.6 1078.45   564.4 1099.19   594.1 1123.47
   623.8 1145.56   633.7 1159.05   643.6 1167.33   663.4 1180.46   693.1 1197.64
#Mann= 3 , 0 , 0
       0     .06       0   307.6    .045       0   327.6     .06       0
Bank Sta=307.6,327.6
XS Rating Curve= 0 ,0
Exp/Cntr=0.3,0.1

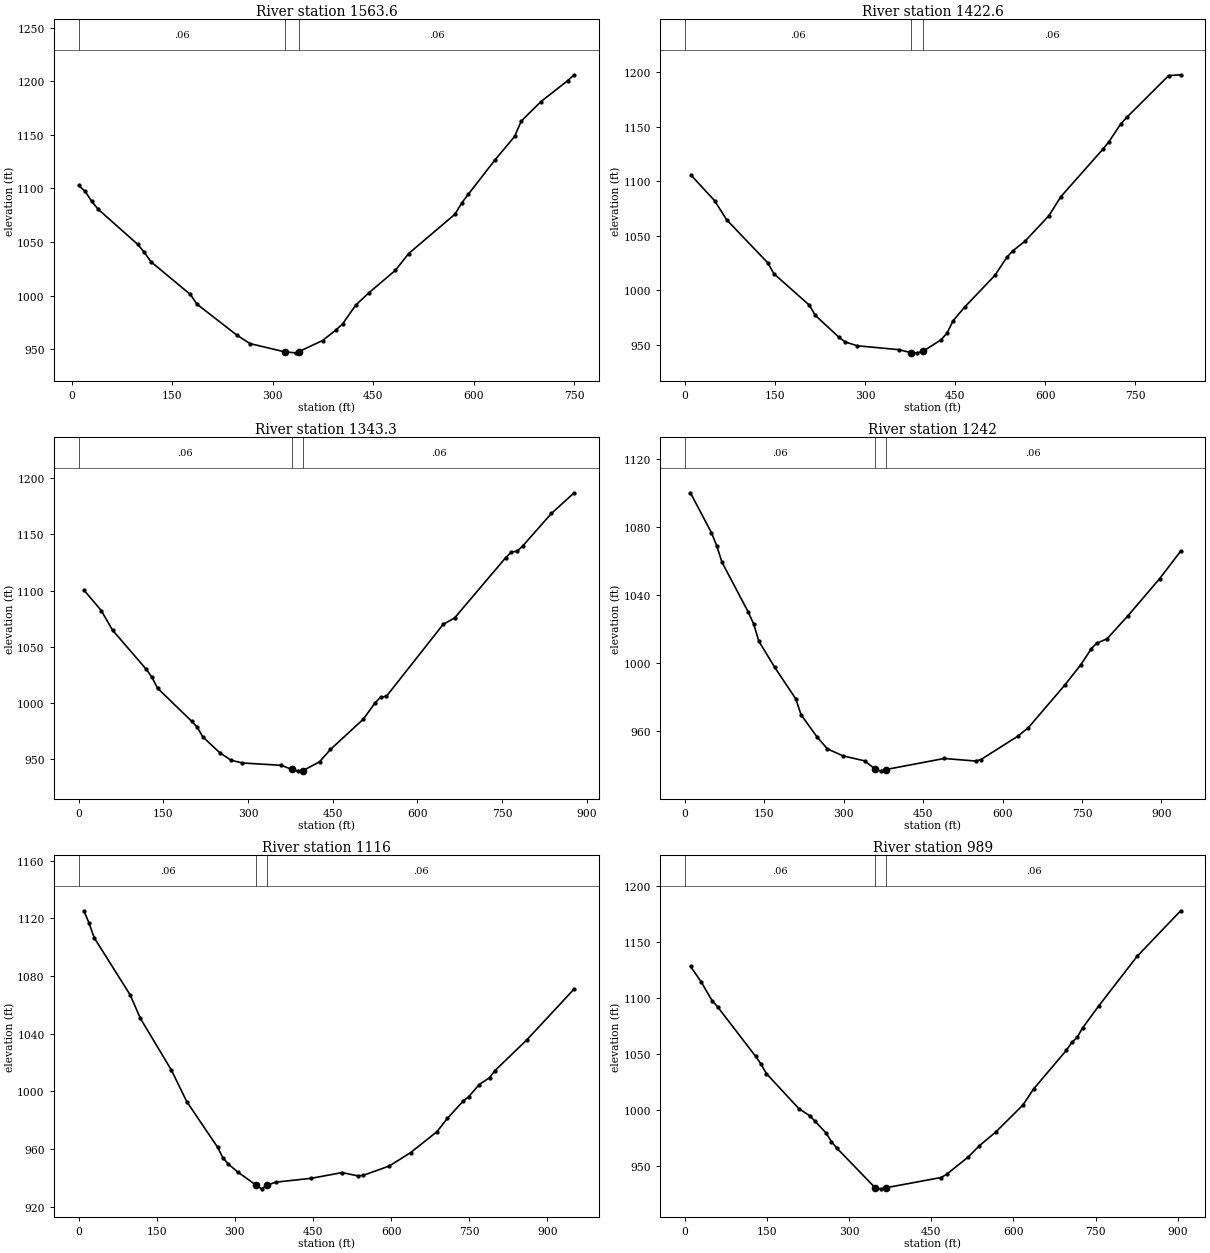
Type RM Length L Ch R = 1 ,1563.6  ,146.6,141,135.4
XS GIS Cut Line= 4
      1663806.21      211923.895     1663620.041      211913.406
     1663363.075      211906.851     1663110.042       212079.91
#Sta/Elev= 30
     9.8 1102.84    19.6 1097.14    29.4 1087.84    39.3 1080.35    98.1 1047.76
     108 1040.28   117.8 1031.58   176.7 1001.03   186.5  992.02   245.8  963.26
   265.6  955.22  318.31  947.35   334.8  946.55  338.52  947.59   374.3  958.05
   394.1  967.88     404  973.42   423.7  990.98   443.5 1002.61   483.1  1023.6
   502.8 1039.19   572.1 1075.92     582 1086.32   591.8 1094.38   631.4 1126.27
   661.1 1148.43     671 1162.79   700.6 1181.06   740.2 1200.43   750.1 1206.01
#Mann= 3 , 0 , 0
     9.8     .06       0  318.31    .045       0  338.52     .06       0
Bank Sta=318.31,338.52
XS Rating Curve= 0 ,0
Exp/Cntr=0.3,0.1

Type RM Length L Ch R = 1 ,1422.6  ,76.3,79.3,82.2
XS GIS Cut Line= 4
      1663818.01      211757.391     1663601.686      211741.658
     1663327.676      211796.722     1663090.376      212024.845
#Sta/Elev= 30
     9.9 1105.59    49.3 1082.07      69 1064.76     138 1024.92   147.9 1015.13
     207  986.23   216.9  976.91   256.8  956.57   266.8  952.46   286.8  948.97
   356.6  945.38   376.6  942.56   386.6  942.49   396.6  943.93   426.5   954.5
   436.5  960.68   446.5  971.96   466.4  984.86   516.3 1013.66   536.3 1030.42
   546.3 1036.25   566.2  1044.9   606.1 1068.36   626.1 1085.88   695.9  1129.3
   705.9 1136.05   725.8 1152.57   735.8  1158.6   805.6 1196.94   825.6  1197.7
#Mann= 3 , 0 , 0
       0     .06       0   376.6    .045       0   396.6     .06       0
Bank Sta=376.6,396.6
XS Rating Curve= 0 ,0
Exp/Cntr=0.3,0.1

Type RM Length L Ch R = 1 ,1343.3  ,86.3,101.3,116.3
XS GIS Cut Line= 4
     1663809.139      211715.888      1663500.14      211693.026
     1663306.186      211708.513     1663073.884       212000.55
#Sta/Elev= 30
      10 1100.12      40 1082.33      60 1064.91   119.9 1030.05   129.9 1023.01
   139.9 1013.26   199.9  984.07   209.9  978.74   219.9  970.08   249.9  955.99
   269.9  949.33   289.9  946.87   358.5  944.79   377.7  941.18   387.7  939.88
   397.7  940.16   426.6  947.91     446  958.92   504.4  985.88   524.6 1000.05
   534.7 1005.29   544.8 1005.95   645.6 1070.02   665.8  1075.7   756.6 1129.43
   766.6 1134.32   776.7 1135.06   786.8 1139.85   837.2 1168.53   877.6 1186.94
#Mann= 3 , 0 , 0
       0     .06       0   377.7    .045       0   397.7     .06       0
Bank Sta=377.7,397.7
XS Rating Curve= 0 ,0
Exp/Cntr=0.3,0.1

Type RM Length L Ch R = 1 ,1242    ,141,126,110.7
XS GIS Cut Line= 4
     1663808.857      211680.501     1663521.737      211649.036
     1663372.277      211566.439     1662961.789      211324.293
#Sta/Elev= 30
      10    1100    49.8 1076.53    59.8 1068.78    69.7 1059.18   119.5 1029.76
   129.5 1022.89   139.4 1012.68   169.3   997.4   209.2  978.79   219.1  969.48
     249  956.58   268.9   949.4   298.9  945.28   339.1   942.4   359.2  937.53
   369.2  936.53   379.2  937.29   489.4  943.79     549  942.29   558.9  943.17
   628.4  956.86   648.3  961.84   717.8  987.13   747.5  998.86   767.4  1008.3
   777.3  1011.5   797.2 1014.18   836.9 1027.79   896.5  1049.5   936.2 1065.66
#Mann= 3 , 0 , 0
       0     .06       0   359.2    .045       0   379.2     .06       0
Bank Sta=359.2,379.2
XS Rating Curve= 0 ,0
Exp/Cntr=0.3,0.1

Type RM Length L Ch R = 1 ,1116    ,112.8,127,141.6
XS GIS Cut Line= 5
     1663838.637      211614.855      1663555.45      211497.598
     1663483.949      211501.839     1663348.959      211527.097
     1662968.427      211314.706
#Sta/Elev= 30
     9.9 1125.18    19.8 1116.85    29.7 1106.59    98.9 1066.93   118.6  1050.6
     178 1014.83   207.6  992.95     267  961.23   276.8   954.1   286.7  949.89
   306.5  943.92   341.3  934.93   351.3  932.53   361.3  934.91   378.1  937.14
   446.8  939.84   505.7  943.78   535.7  941.54   545.9  941.82   596.5  948.39
   637.1  957.57   687.8  972.11     708  981.35   738.4  993.43   748.6  996.27
   768.8 1004.69   789.1 1009.64   799.2 1014.44     860 1035.59   951.3 1071.02
#Mann= 3 , 0 , 0
       0     .06       0   341.3    .045       0   361.3     .06       0
Bank Sta=341.3,361.3
XS Rating Curve= 0 ,0
Exp/Cntr=0.3,0.1

Type RM Length L Ch R = 1 ,989     ,81.4,87.7,94
XS GIS Cut Line= 4
     1663844.231      211605.309     1663635.834      211422.376
     1663457.367       211330.93     1663092.998      211107.109
#Sta/Elev= 30
     9.9 1128.15    29.7 1114.11    49.5 1097.38    59.4 1092.04   128.7 1047.88
   138.6 1040.94   148.6 1032.33     208    1001   227.8  994.65   237.7  989.61
   257.5  979.32   267.4  971.53   277.3  965.74   347.5   930.2   357.5  929.35
   367.5  930.37   467.8  939.48   477.8  942.29   517.6  957.91   537.5   967.8
   567.3  979.97   617.1 1004.14   636.9 1018.67   696.6 1053.15   706.6  1060.2
   716.5 1064.84   726.4 1073.23   756.3 1093.16   825.9 1137.15   905.5 1177.89
#Mann= 3 , 0 , 0
       0     .06       0   347.5    .045       0   367.5     .06       0
Bank Sta=347.5,367.5
XS Rating Curve= 0 ,0
Exp/Cntr=0.3,0.1