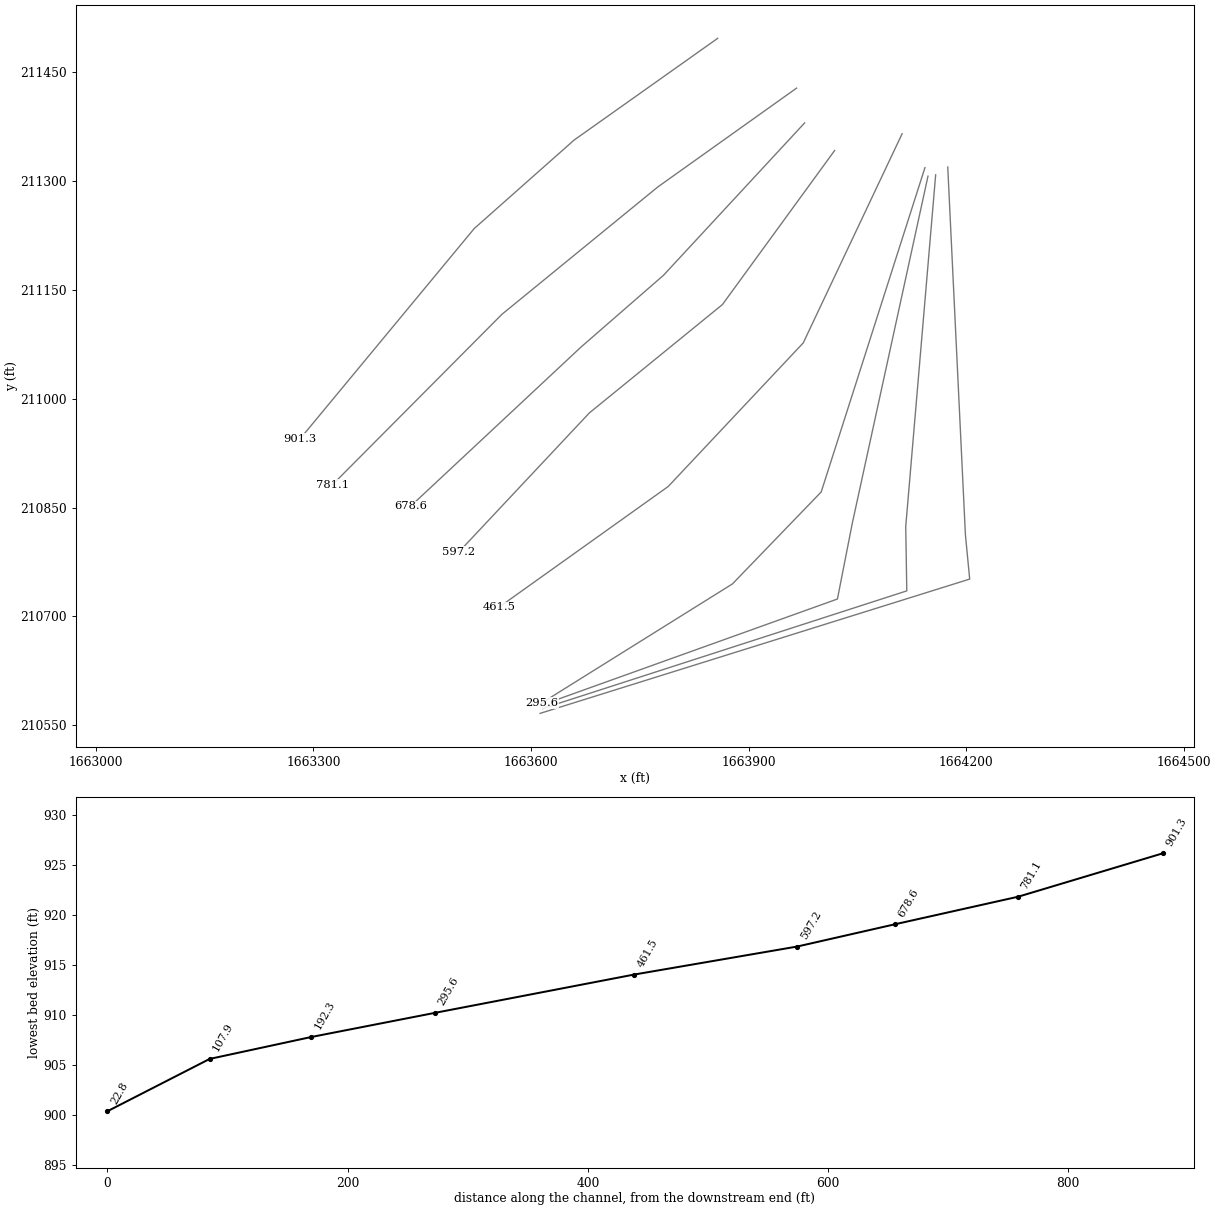
HEC-RAS study np4.prj: np4

--- np4.g01 (geometry) --- (continued)

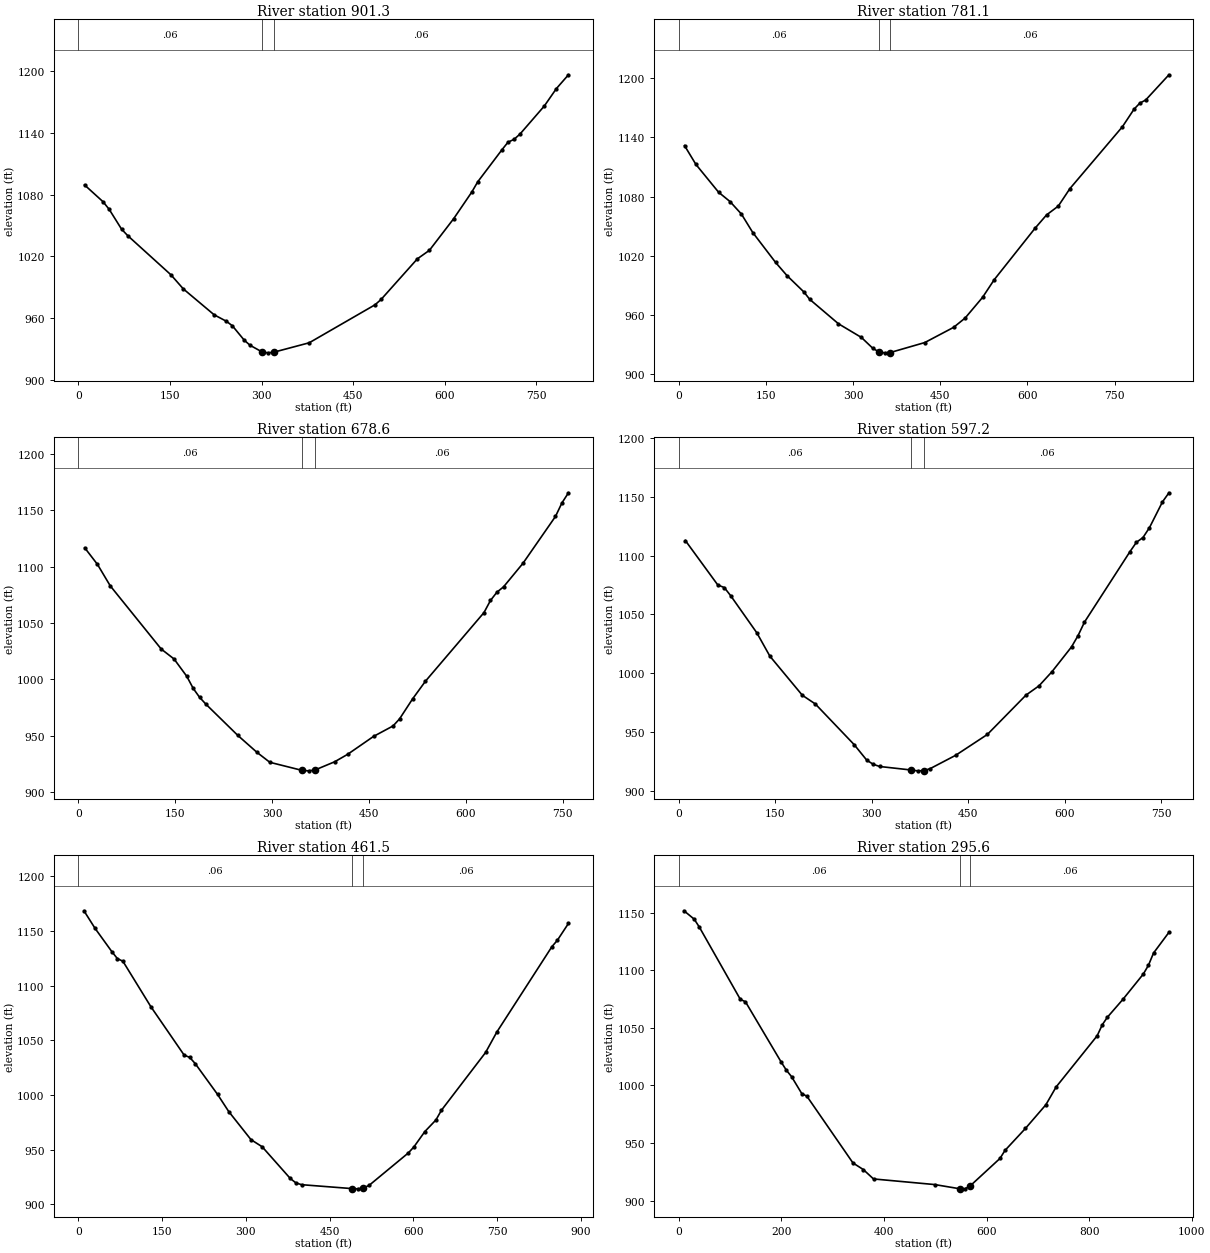
Type RM Length L Ch R = 1 ,901.3   ,121.2,120.2,119.3
XS GIS Cut Line= 4
     1663857.366      211496.954     1663659.397      211356.671
     1663521.737      211234.743     1663281.814      210945.001
#Sta/Elev= 30
    10.1 1089.43    40.4 1073.11    50.5 1065.68    70.8 1046.39    80.9 1040.07
   151.6 1002.03   171.9  988.31   222.4  963.12   242.6  956.78   252.3   952.4
   271.7  938.43   281.3  933.44   300.4  927.17   310.4  926.13   320.4   926.8
   378.1  935.91   485.9  972.86   495.8  978.04   555.2 1017.53     575 1025.86
   614.6 1056.53   644.3 1082.44   654.2 1092.54   693.8 1123.65   703.7    1131
   713.6 1133.76   723.5 1139.02   763.1 1166.15   782.9 1183.11   802.7 1196.56
#Mann= 3 , 0 , 0
       0     .06       0   300.4    .045       0   320.4     .06       0
Bank Sta=300.4,320.4
XS Rating Curve= 0 ,0
Exp/Cntr=0.3,0.1

Type RM Length L Ch R = 1 ,781.1   ,101.6,102.4,103.3
XS GIS Cut Line= 4
     1663966.159      211428.317     1663774.745      211291.967
     1663559.733      211116.286     1663326.365      210881.608
#Sta/Elev= 30
     9.8 1131.71    29.4 1112.63    68.5 1084.43    88.1 1075.03   107.7 1062.38
   127.3 1043.61   166.5  1013.4   186.1 1000.06   215.4  983.38   225.2  976.01
   274.7  951.26   314.3  937.38   334.2   926.2     344  922.98     354   921.8
     364  922.14   423.4  932.23     473  947.63   492.8  957.06   522.7  977.92
   542.8  995.85     613 1047.91     633 1061.53   653.1 1070.42   673.1 1088.13
   763.4 1150.74   783.5 1168.58   793.5 1174.75   803.5 1177.86   843.6 1203.45
#Mann= 3 , 0 , 0
       0     .06       0     344    .045       0     364     .06       0
Bank Sta=344,364
XS Rating Curve= 0 ,0
Exp/Cntr=0.3,0.1

Type RM Length L Ch R = 1 ,678.6   ,82.3,81.5,80.6
XS GIS Cut Line= 4
     1663977.281      211380.341      1663782.59      211170.163
      1663669.02      211071.342     1663433.768      210851.577
#Sta/Elev= 30
     9.9 1116.58    29.6 1101.93    49.4 1082.92   128.4  1026.9   148.2 1018.14
   167.9  1002.8   177.8  992.14   187.7  984.21   197.6  978.05     247   950.4
   276.6  935.43   296.5  926.62   346.7  919.42   356.7  919.05   366.7  919.86
   396.9  927.07     417  933.67   457.2  949.57   487.3   958.8   497.4  965.04
   517.5  982.69   537.6  998.51   628.2 1059.27   638.2 1069.96   648.3 1077.37
   658.4    1082   688.5 1102.87   738.9 1144.42   748.9 1156.41     759 1165.38
#Mann= 3 , 0 , 0
       0     .06       0   346.7    .045       0   366.7     .06       0
Bank Sta=346.7,366.7
XS Rating Curve= 0 ,0
Exp/Cntr=0.3,0.1

Type RM Length L Ch R = 1 ,597.2   ,132,135.7,139.4
XS GIS Cut Line= 4
     1664018.625       211342.25     1663863.921      211129.859
     1663680.374      210980.399      1663500.76      210788.986
#Sta/Elev= 30
    10.1 1113.01    60.6 1075.12    70.7 1072.95    80.8 1065.85   121.3 1034.34
   141.5 1014.53     192   981.2   212.2  973.78   272.6  939.14   292.3  925.83
   302.2  922.43   312.1  920.53   361.2  917.53   371.2  916.82   381.2  916.99
     391  918.77   430.4  930.06   479.7  947.82   539.8  981.36     560  989.23
   580.2 1001.31   610.5 1022.38   620.6 1031.92   630.7 1043.54   701.4 1103.54
   711.5 1111.54   721.6 1115.52   731.7 1123.96   751.9 1145.91     762 1153.68
#Mann= 3 , 0 , 0
       0     .06       0   361.2    .045       0   381.2     .06       0
Bank Sta=361.2,381.2
XS Rating Curve= 0 ,0
Exp/Cntr=0.3,0.1

Type RM Length L Ch R = 1 ,461.5   ,166.6,165.9,165.2
XS GIS Cut Line= 4
     1664111.685      211365.386     1663975.336      211076.955
     1663789.167      210878.986     1663555.799      210712.482
#Sta/Elev= 30
      10 1168.38    29.9 1152.29    59.8 1131.11    69.8 1124.68    79.8 1122.18
   129.6 1080.81   189.4 1036.36   199.4 1034.25   209.4 1028.47   249.2 1000.43
   269.2  984.75   309.1  959.01   329.1  952.51   379.4  923.52   389.5  919.46
   399.6  917.82   490.2  914.23   500.2  914.02   510.2  914.84   520.3  917.08
   590.8  946.85   600.7  952.33   620.4  966.44   640.2  977.02   650.1  985.94
   729.2 1038.81     749 1057.24   847.8  1135.5   857.7 1141.45   877.5 1156.82
#Mann= 3 , 0 , 0
       0     .06       0   490.2    .045       0   510.2     .06       0
Bank Sta=490.2,510.2
XS Rating Curve= 0 ,0
Exp/Cntr=0.3,0.1

Type RM Length L Ch R = 1 ,295.6   ,88,103.2,118.4
XS GIS Cut Line= 4
     1664143.175      211318.651     1664000.143      210871.488
     1663877.723      210744.644     1663614.821      210580.529
#Sta/Elev= 30
      10 1151.59      30 1144.29      40  1137.4   119.9 1074.69   129.9  1072.6
   199.8 1020.07   209.8 1013.09   219.8  1007.6   239.7  992.88   249.7  990.59
   339.6  932.63   359.6  926.97   379.6  918.78   498.9   913.9   547.6  910.27
   557.6  910.19   567.6  912.54   626.2  936.58     636  943.54   675.8  962.61
   715.7  983.18   735.7  998.64   815.7 1043.05   825.7 1052.63   835.7  1059.2
   865.7 1074.57   905.7 1096.64   915.7 1104.26   925.7 1114.94   955.7 1132.87
#Mann= 3 , 0 , 0
       0     .06       0   547.6    .045       0   567.6     .06       0
Bank Sta=547.6,567.6
XS Rating Curve= 0 ,0
Exp/Cntr=0.3,0.1

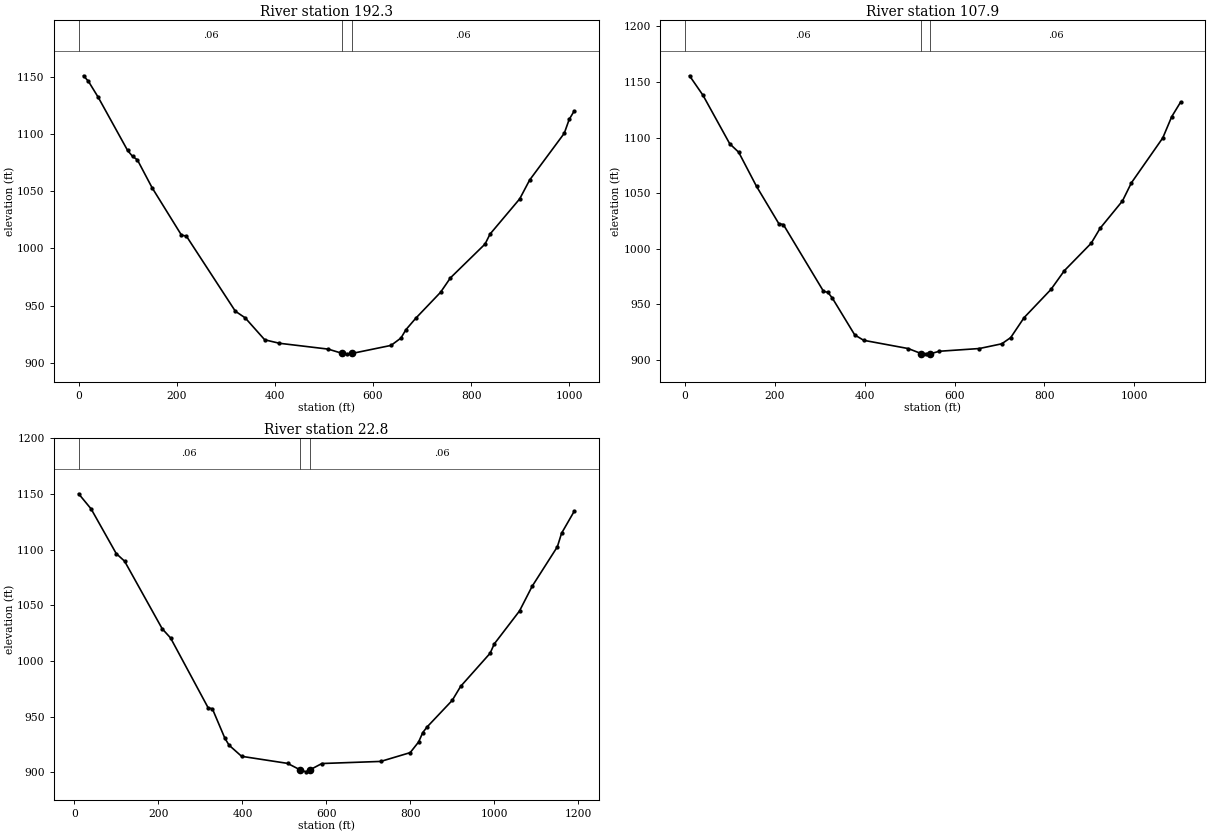
Type RM Length L Ch R = 1 ,192.3   ,79.2,84.5,89.7
XS GIS Cut Line= 4
     1664147.366      211306.912     1664043.137      210829.033
     1664022.488      210723.821     1663633.106      210584.194
#Sta/Elev= 30
      10 1150.75      20 1145.89    39.9 1131.97    99.8 1085.51   109.8 1080.36
   119.8 1077.25   149.7 1052.96   209.6 1011.49   219.6 1010.68   319.4  945.02
   339.4  939.24   379.3  920.03   409.3     917   508.6   911.9   537.6  908.13
   547.6  907.77   557.6  908.15   636.7  915.14   656.9  921.55     667  928.83
   687.1  938.86   737.6  961.52   757.8  974.16   828.4 1003.73   838.5 1012.41
     899  1043.2   919.2 1059.63   989.8 1100.49   999.9 1112.68    1010 1119.93
#Mann= 3 , 0 , 0
       0     .06       0   537.6    .045       0   557.6     .06       0
Bank Sta=537.6,557.6
XS Rating Curve= 0 ,0
Exp/Cntr=0.3,0.1

Type RM Length L Ch R = 1 ,107.9   ,83.1,85.1,83.4
XS GIS Cut Line= 4
      1664157.96      211308.806     1664116.662      210823.553
     1664118.137      210735.057     1663615.922      210572.815
#Sta/Elev= 30
     9.9 1155.61    39.8 1138.09    99.4 1094.46   119.3 1086.88     159 1056.19
   208.7 1022.63   218.7 1021.86   308.1  961.85     318  960.81     328  955.61
   377.7  922.58   397.6  917.75   496.8  910.33   526.2  905.74   536.2  905.58
   546.2  905.62   565.7  907.89   655.2  910.36     705   914.6   724.9  920.17
   754.8  938.15   814.5  963.46   844.4  980.36   904.1 1005.01     924 1018.47
   973.8 1043.07   993.7 1059.37  1063.5 1099.71  1083.4 1118.81  1103.3 1131.99
#Mann= 3 , 0 , 0
       0     .06       0   526.2    .045       0   546.2     .06       0
Bank Sta=526.2,546.2
XS Rating Curve= 0 ,0
Exp/Cntr=0.3,0.1

Type RM Length L Ch R = 1 ,22.8    ,25,22.8,24.3
XS GIS Cut Line= 4
     1664174.616        211319.5     1664198.959      210812.601
      1664204.87       210751.31     1663612.502      210566.136
#Sta/Elev= 30
      10 1150.17    39.8 1136.52    99.5 1096.45   119.4 1089.62     209 1028.86
   228.9 1020.62   318.4  957.83   328.4     957   358.2  930.49   368.2  924.27
     398  914.29   507.5  907.94  537.12  902.17   551.5  900.35   561.5  902.34
   589.1  907.82   729.2  909.71   799.3  917.61   819.3  927.15   829.3  935.63
   839.3  940.58   899.4  964.56   919.4  977.13   989.5 1006.85   999.5 1015.29
  1059.6 1044.91  1089.6 1067.02  1149.7 1102.58  1159.7 1114.72  1189.7 1134.39
#Mann= 3 , 0 , 0
      10     .06       0  537.12    .045       0   561.5     .06       0
Bank Sta=537.12,561.5
XS Rating Curve= 0 ,0
Exp/Cntr=0.3,0.1

Chan Stop Cuts=-1
Use User Specified Reach Order=0